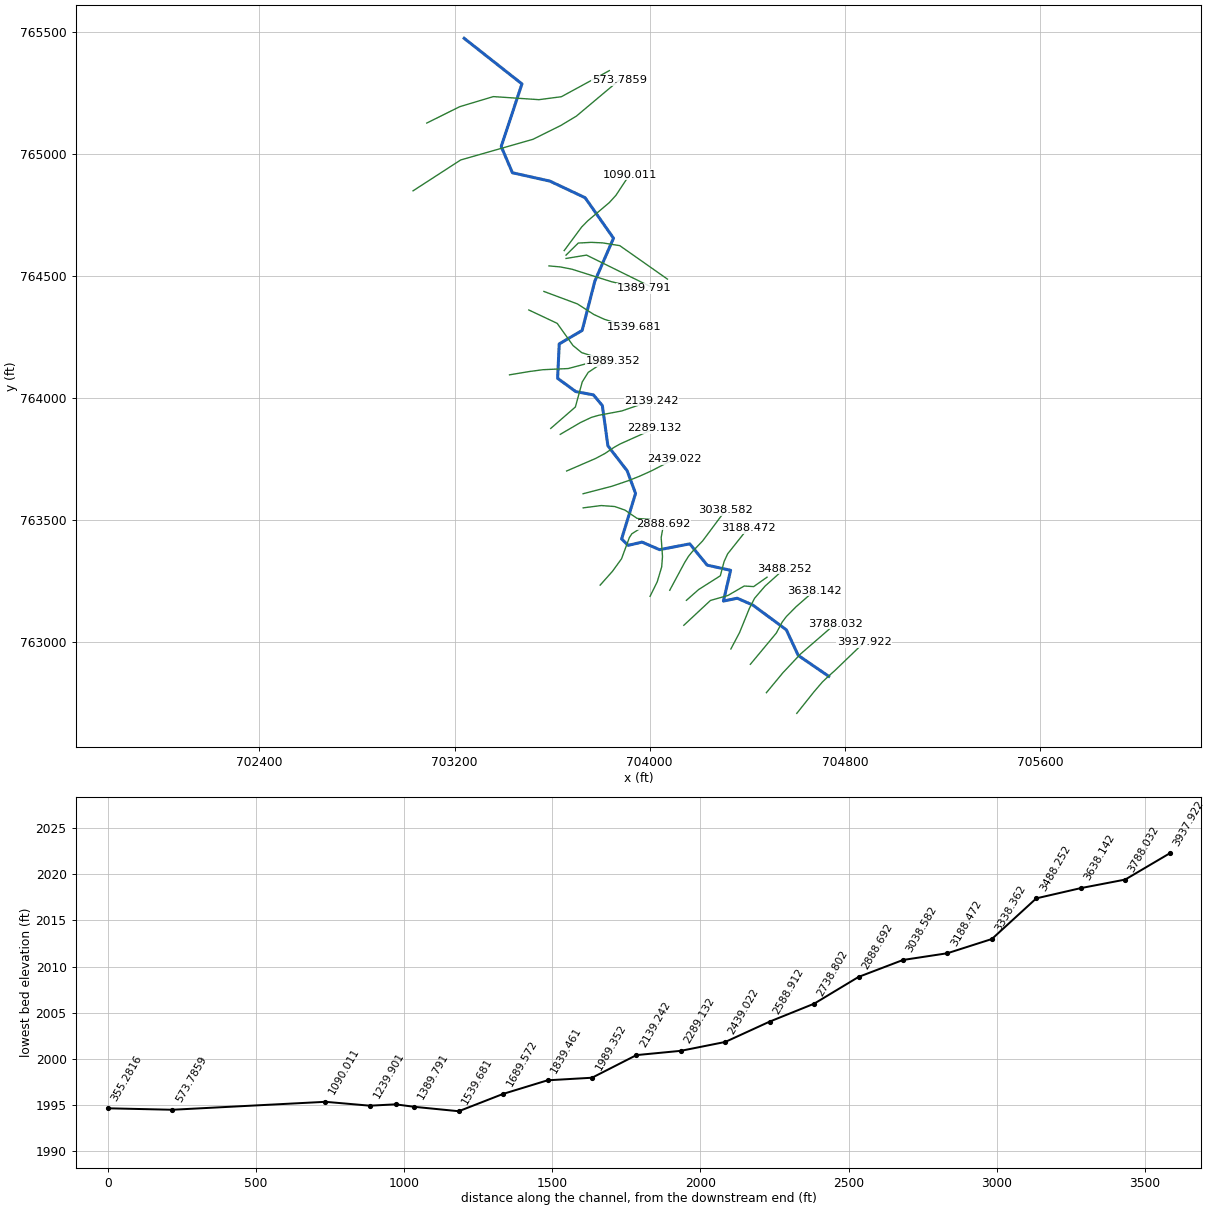
--- 14449_ras.prj (project) ---

Proj Title=14449
Current Plan=p01
Default Exp/Contr=0.3,0.1
English Units
Geom File=g01
Flow File=f01
Plan File=p01
Y Axis Title=Elevation
X Axis Title(PF)=Main Channel Distance
X Axis Title(XS)=Station
BEGIN DESCRIPTION:
RFD model 14449 exported to HEC-RAS
END DESCRIPTION:

--- 14449_ras.p01 (plan) ---

Plan Title=Plan 01
Program Version=4.10
Short Identifier=Plan 01
Geom File=g01
Flow File=f01
Subcritical Flow
Calc Critical at every XS
Secant Critical Depth

--- 14449_ras.f01 (steady flow) ---

Flow Title=Flow 01
Program Version=5.01
Number of Profiles= 6
Profile Names=10yr,25yr,50yr,100yr,100plus,500yr
River Rch & RM=14449,23,3937.922
  118.33  200.08  279.94     358  522.69 1012.27
River Rch & RM=14449,23,3488.252
  122.67  207.48  290.34  371.34  542.16 1044.76
River Rch & RM=14449,23,3338.362
  125.33  212.01  296.71   379.5  554.07 1064.56
River Rch & RM=14449,23,3038.582
  128.97  218.19  305.41  390.66  570.37 1091.55
River Rch & RM=14449,23,2888.692
  130.62     221  309.35  395.71  577.74 1103.73
River Rch & RM=14449,23,2738.802
  179.95  305.08  427.72  547.65  799.56  1461.5
River Rch & RM=14449,23,2588.912
  180.87  306.64  429.92  550.48   803.7 1468.03
River Rch & RM=14449,23,2439.022
  196.08  332.55  466.41  597.31  872.08 1575.18
River Rch & RM=14449,23,2289.132
  197.28  334.61  469.31  601.03   877.5 1583.63
River Rch & RM=14449,23,2139.242
  205.36  348.39  488.72  625.96   913.9 1640.19
River Rch & RM=14449,23,1989.352
  208.64  353.98   496.6  636.07  928.67 1663.02
River Rch & RM=14449,23,1839.461
  251.08  426.44  598.76   767.3 1120.26 1955.39
River Rch & RM=14449,23,1689.572
  253.65  430.83  604.95  775.25 1131.86 1972.84
River Rch & RM=14449,23,1539.681
  254.79  432.77   607.7  778.77 1137.01 1980.57
River Rch & RM=14449,23,1389.791
  261.33  443.94  623.43  798.99 1166.52 2024.82
River Rch & RM=14449,23,1239.901
   261.9  444.91   624.8  800.74 1169.08 2028.65
Boundary for River Rch & Prof#=14449,23,1
Up Type= 0
Dn Type= 2
Boundary for River Rch & Prof#=14449,23,2
Up Type= 0
Dn Type= 2
Boundary for River Rch & Prof#=14449,23,2
Up Type= 0
Dn Type= 2
Boundary for River Rch & Prof#=14449,23,2
Up Type= 0
Dn Type= 2
Boundary for River Rch & Prof#=14449,23,2
Up Type= 0
Dn Type= 2
Boundary for River Rch & Prof#=14449,23,2
Up Type= 0
Dn Type= 2

--- 14449_ras.g01 (geometry) ---

Geom Title=14449
Program Version=4.10

River Reach=14449,23
Reach XY= 30
704733.623418957762859.846400052704608.623418957762945.401955634
704559.734530032763050.401955634704423.067863375763151.513066739
704358.623418957763179.846400052  704301.9567523 763168.17973341
704331.401196718  763294.2908445704235.290085614763315.401955619
704164.178974479763402.624177828704040.290085644763378.735288948
703968.623418957763409.846400067  703911.9567523763396.513066739
703884.734530061763422.624177828  703941.9567523763609.290844515
703907.512307823763702.068622276703828.623418897763804.290844515
703805.845641166763969.290844515703769.178974479764013.179733396
  703696.9567523764026.513066724703622.512307823764080.957511172
703629.178974479764222.068622291703723.067863405764277.068622291
703775.012307823764479.082511172703851.555137336764655.111557662
703735.213080913764820.997807622703591.145528674764888.946444094
703437.371121526764923.285727888703391.364177078765030.924616799
703476.344885081765287.350684822703239.659953147765474.098353654

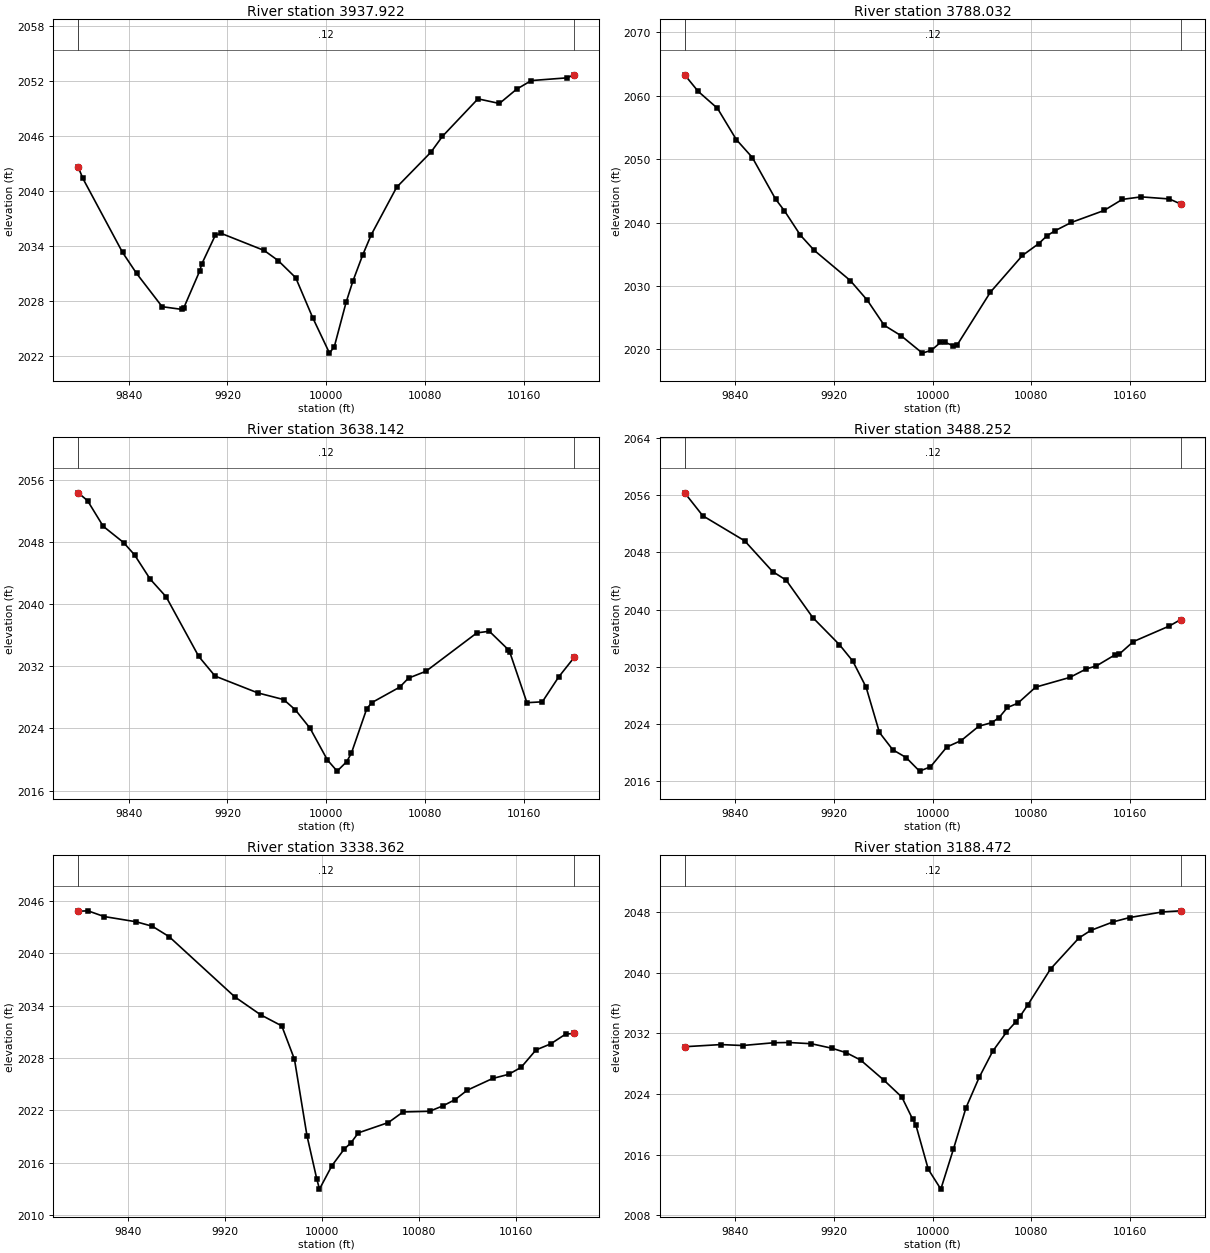
Type RM Length L Ch R = 1 ,3937.922,149.890000,149.890000,149.890000
XS GIS Cut Line= 6
704602.640659673762707.998072567704673.105486725762796.538966322
704707.884629864762836.975753422704732.214371983762859.967175491
704758.691661362762883.594816026704878.631535984762999.068485885
#Sta/Elev= 30
9799.0312042.611 9802.822041.3669834.9382033.2869846.3212030.9819867.055 2027.34
9883.1142027.0449884.6622027.2339897.4422031.2299899.1732032.0139910.2232035.181
9915.095 2035.35 9949.732033.4939961.1022032.3849975.3152030.5099989.0742026.141
10002.692022.26110006.612022.97510016.112027.801 10021.62030.11510029.532032.973
10036.512035.20410057.132040.40810084.892044.24110094.192045.96810123.022050.077
10140.41 2049.57 10154.32051.12810166.282052.07610195.112052.37310200.982052.704
#Mann= 3 , 0 , 0
9799.031    0.12       09799.031    0.12       010200.98    0.12       0
#XS Ineff= 2 , 0
       09944.659                       0
Bank Sta=9799.031,10200.98
Exp/Cntr=0.3,0.1

Type RM Length L Ch R = 1 ,3788.032,149.890100,149.890100,149.890100
XS GIS Cut Line= 6
704478.045979186762792.775136471704545.247156837762873.917298865
 704610.02337131762942.884918652704611.324954058762944.403431855
704617.394775853762950.799645694704761.918490378763075.916869379
#Sta/Elev= 30
9799.0262063.3189809.9282060.7159825.6062058.0339840.8672053.1089853.8512050.277
9872.6392043.731 9879.822041.8899892.8042038.0289903.9952035.6399933.2352030.871
9947.0252027.7729960.7442023.8159974.4632022.1649991.6622019.423    99992019.874
10006.342021.10710009.822021.15310016.242020.61510019.882020.71510046.792029.032
10072.78 2034.8310086.01  2036.710092.632037.92610099.242038.73310112.462040.038
10138.922041.92110153.742043.67310169.022044.06910191.832043.74110200.982042.951
#Mann= 3 , 0 , 0
9799.026    0.12       09799.026    0.12       010200.98    0.12       0
#XS Ineff= 2 , 0
       0                               0
Bank Sta=9799.026,10200.98
Exp/Cntr=0.3,0.1

Type RM Length L Ch R = 1 ,3638.142,149.890000,149.890000,149.890000
XS GIS Cut Line= 6
704412.322029786762909.062583412704518.715100019763037.049957898
704542.666044082 763081.96361509704559.951259933763104.935618682
704600.793989953763146.038936428704674.449916617763210.112023092
#Sta/Elev= 30
9799.0572054.2899806.5932053.2859819.286 2049.999835.8822047.886 9844.672046.314
9857.3632043.1919870.2882040.9179896.7292033.2469909.9492030.7239944.5722028.559
 9965.542027.6999975.0352026.3719986.9062024.016   100012019.92510008.852018.498
10016.592019.71310020.392020.803 10032.92026.548 10037.12027.32210059.522029.297
10066.682030.45810080.872031.34510122.11 2036.2810132.172036.48610147.412034.139
10148.622033.86110162.642027.29910175.132027.41210188.382030.612 10200.92033.117
#Mann= 3 , 0 , 0
9799.057    0.12       09799.057    0.12       0 10200.9    0.12       0
#XS Ineff= 2 , 0
       0                               0
Bank Sta=9799.057,10200.9
Exp/Cntr=0.3,0.1

Type RM Length L Ch R = 1 ,3488.252,149.890100,149.890100,149.890100
XS GIS Cut Line= 6
704332.576813983762972.047352647704367.976134479763038.931595923
704408.385892839763138.100797401704429.691047392763179.742065204
704472.381859864763229.306951428704551.890666471763300.573540412
#Sta/Elev= 30
9799.0522056.3269813.7072053.121 9847.652049.6129870.2782045.3169881.2792044.108
9902.8762038.8699924.4732035.0799935.2712032.7849946.0692029.1349956.8682022.799
9967.6662020.3799978.4652019.2949989.3492017.389 9998.252017.991 10011.52020.768
10023.142021.66810037.362023.66810047.94 2024.1810053.732024.86310060.612026.297
10068.96 2026.8810083.462029.13910111.122030.49610124.542031.69210132.662032.106
10147.652033.649 10151.4 2033.7910162.632035.51110191.692037.68510200.942038.584
#Mann= 3 , 0 , 0
9799.052    0.12       09799.052    0.12       010200.94    0.12       0
#XS Ineff= 2 , 0
       0                               0
Bank Sta=9799.052,10200.94
Exp/Cntr=0.3,0.1

Type RM Length L Ch R = 1 ,3338.362,149.890000,149.890000,149.890000
XS GIS Cut Line= 6
 704139.70596078  763068.9940584704248.984095871763170.769731402
704320.222393334763191.069382831704387.127800643763229.862482741
704425.847499549763227.442501545704480.700406283763266.162200421
#Sta/Elev= 30
9799.1022044.8229807.155 2044.879820.3442044.2189846.8852043.6159860.1562043.103
9874.0022041.9129928.2232035.0019949.4192032.9589966.8272031.6859977.285 2027.86
9987.5912019.1129995.6292014.1699997.8982012.98310008.162015.67510018.382017.587
10023.722018.26910029.952019.43210054.722020.61510066.732021.82410088.562021.901
10099.482022.51510109.69 2023.2410119.712024.322 10140.62025.66210153.712026.135
10164.052026.93510176.292028.92910188.392029.62210200.77 2030.7510207.742030.823
#Mann= 3 , 0 , 0
9799.102    0.12       09799.102    0.12       010207.74    0.12       0
#XS Ineff= 2 , 0
       0                               0
Bank Sta=9799.102,10207.74
Exp/Cntr=0.3,0.1

Type RM Length L Ch R = 1 ,3188.472,149.890100,149.890100,149.890100
XS GIS Cut Line= 6
 704150.31576206763171.328607252704200.341249671 763215.31894412
704289.300837863763271.800287133704304.656830695763329.973568848
704319.359063928 763361.79225578704402.440443736763466.261861257
#Sta/Elev= 30
9799.235 2030.229828.5452030.5039846.149 2030.389871.4892030.7469883.4532030.777
9901.7722030.6169918.693 2030.01 9930.212029.4229941.727 2028.46 9960.632025.798
9975.075 2023.589983.7122020.7049986.3442019.9529996.4962014.05110006.662011.442
10016.852016.72110027.052022.18410037.662026.16310048.682029.63110059.692032.109
10067.172033.46210071.082034.29410077.032035.72610095.472040.47210118.452044.558
 10128.12045.56110146.372046.69210159.562047.25410185.952047.99110200.81 2048.14
#Mann= 3 , 0 , 0
9799.235    0.12       09799.235    0.12       010200.81    0.12       0
#XS Ineff= 2 , 0
       0                               0
Bank Sta=9799.235,10200.81
Exp/Cntr=0.3,0.1

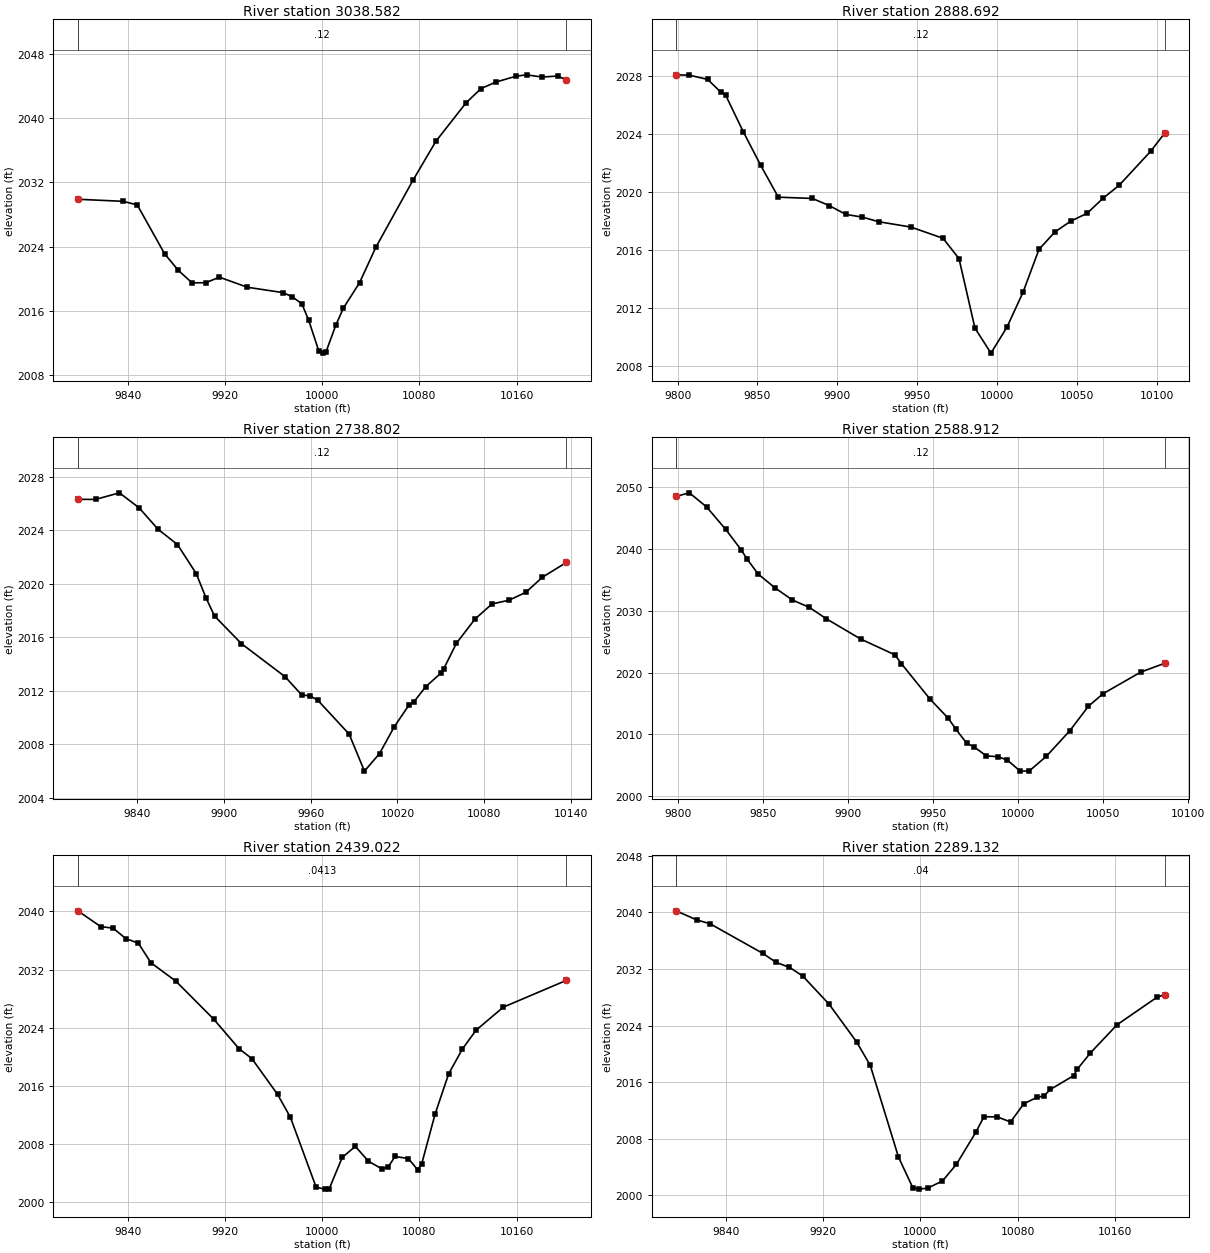
Type RM Length L Ch R = 1 ,3038.582,149.890000,149.890000,149.890000
XS GIS Cut Line= 6
704081.994165023 763212.52886247704142.697408779763325.415384246
704159.113005493763352.008142794  704172.7108797763368.798673918
704216.817582639763414.731916664 704310.71901928763540.704700854
#Sta/Elev= 30
9799.0452029.8949836.4352029.6359847.9362029.1869870.4622023.0879881.7242021.033
9892.9872019.4769904.2492019.4879915.5122020.1819938.5062018.9249967.8482018.256
9975.2122017.7569983.3142016.8699988.9352014.8269997.3532010.946   100012010.711
10003.262010.881 10011.32014.20210017.542016.32810030.882019.50610044.162023.888
10074.722032.24910093.632037.12310118.372041.90310130.742043.69510143.112044.512
10159.472045.23310168.222045.40810180.962045.131 10193.72045.25710200.972044.785
#Mann= 3 , 0 , 0
9799.045    0.12       09799.045    0.12       010200.97    0.12       0
#XS Ineff= 2 , 0
       0                               0
Bank Sta=9799.045,10200.97
Exp/Cntr=0.3,0.1

Type RM Length L Ch R = 1 ,2888.692,149.890100,149.890100,149.890100
XS GIS Cut Line= 6
704001.389799965763187.638309206704030.809445299763247.414752492
704048.937719128 763308.00228059704052.332062287763350.795961016
704046.842976565763428.526624192704056.579445431763482.484866756
#Sta/Elev= 28
9799.0612028.105 9807.422028.0819818.7752027.7879827.135  2026.99830.0382026.707
9841.0452024.1869852.0522021.8479863.0582019.6519884.3962019.5639895.0192019.065
9905.3752018.4619915.6662018.2739925.9572017.9559946.1822017.5849966.228 2016.81
9976.236 2015.419986.2492010.5979996.2612008.87510006.282010.66610016.322013.073
10026.362016.04710036.392017.25310046.432018.00710056.462018.53310066.482019.575
10076.592020.47610096.452022.83810105.082024.079
#Mann= 3 , 0 , 0
9799.061    0.12       09799.061    0.12       010105.08    0.12       0
#XS Ineff= 2 , 0
       0                               0
Bank Sta=9799.061,10105.08
Exp/Cntr=0.3,0.1

Type RM Length L Ch R = 1 ,2738.802,149.890000,149.890000,149.890000
XS GIS Cut Line= 6
703796.875342892 763233.53517113703847.182320112763290.086012346
703884.467686358763341.525778956703916.444450884763428.175338312
703926.433204772763443.731392136703999.380186322763490.524036118
#Sta/Elev= 30
9799.0542026.3089811.2772026.3019827.7832026.7959841.3682025.6779854.5512024.064
9867.9352022.9249880.9372020.7469887.5812018.9559893.5442017.5789912.1832015.508
9942.2922013.0419953.7612011.6829959.8232011.5919964.9932011.2729986.625 2008.74
9997.1972005.97410007.652007.29210017.75 2009.2810028.112010.93910031.422011.162
10039.532012.28710049.912013.29310051.952013.61810060.822015.54510073.562017.345
10085.352018.47810097.192018.76410108.712019.34710120.222020.47910136.792021.586
#Mann= 3 , 0 , 0
9799.054    0.12       09799.054    0.12       010136.79    0.12       0
#XS Ineff= 2 , 0
       0                               0
Bank Sta=9799.054,10136.79
Exp/Cntr=0.3,0.1

Type RM Length L Ch R = 1 ,2588.912,149.890100,149.890100,149.890100
XS GIS Cut Line= 6
703727.363042589763550.137601216703801.110300011763559.644427875
703856.521037791763555.587964392  703898.5880474763540.948821087
703948.450112098763506.781987112703998.951763562763503.162507681
#Sta/Elev= 30
9799.1082048.5559806.854 2049.139816.9962046.8449828.233  2043.29837.2812039.908
9840.5912038.4749847.3482035.9529857.3792033.694 9867.412031.7689877.4292030.557
 9887.43 2028.719907.4872025.4459927.6522022.8789931.504 2021.43 9948.292015.704
9959.0642012.5799963.579 2010.799969.9462008.5169973.851 2008.029981.4372006.496
9988.3312006.3739993.7082005.81710001.272004.03410006.58 2004.0610016.61 2006.43
10030.512010.60610041.392014.56410049.982016.58410072.03 2020.0710086.162021.512
#Mann= 3 , 0 , 0
9799.108    0.12       09799.108    0.12       010086.16    0.12       0
#XS Ineff= 2 , 0
       0                               0
Bank Sta=9799.108,10086.16
Exp/Cntr=0.3,0.1

Type RM Length L Ch R = 1 ,2439.022,149.890000,149.890000,149.890000
XS GIS Cut Line= 6
703726.816100192763607.995435927703843.959221084763638.381713441
703913.059862774763661.710185744703957.910758808763679.628205697
704006.458017439763701.509081672704101.109885752763750.220387481
#Sta/Elev= 30
9799.0242040.0899817.8092037.923 9828.142037.6989838.471 2036.279848.8022035.646
9859.1332032.9569879.7952030.4029910.7882025.1999931.6972021.1299942.2512019.762
 9963.362014.8529973.9152011.7049995.0572002.10610002.022001.82710005.81 2001.85
10016.592006.19110027.362007.70310038.142005.65810049.05 2004.6310054.352004.851
10060.022006.32610070.992006.02110078.682004.48310081.962005.29710092.932012.127
10104.132017.67610115.382021.07310126.622023.66910149.122026.84610200.98 2030.53
#Mann= 3 , 0 , 0
9799.024  0.0413       09799.024  0.0413       010200.98  0.0413       0
#XS Ineff= 2 , 0
       0                               0
Bank Sta=9799.024,10200.98
Exp/Cntr=0.3,0.1

Type RM Length L Ch R = 1 ,2289.132,149.890100,149.890100,149.890100
XS GIS Cut Line= 6
703659.445498771763701.204043891703777.804404975763752.344116739
703816.114930864763772.642482923703855.022267934763798.737693178
703878.899639265763812.142788726704020.743408363763875.625193523
#Sta/Elev= 30
9799.0432040.2179815.9882038.9299826.8812038.3969870.4552034.1919881.3492032.915
9892.2422032.2329903.1362031.0089924.9232027.0039947.4382021.7029958.7552018.361
9981.9782005.3939993.7752001.052    99992000.86510006.052001.01110018.162002.019
10029.632004.37610045.572008.89410052.252011.09510063.212011.08810074.16 2010.36
10085.12 2012.9510096.072013.84310101.522014.04310107.032014.967   101262016.908
10128.942017.792 10139.92020.12910161.812024.10910194.682028.00210200.972028.371
#Mann= 3 , 0 , 0
9799.043    0.04       09799.043    0.04       010200.97    0.04       0
#XS Ineff= 2 , 0
       0                               0
Bank Sta=9799.043,10200.97
Exp/Cntr=0.3,0.1

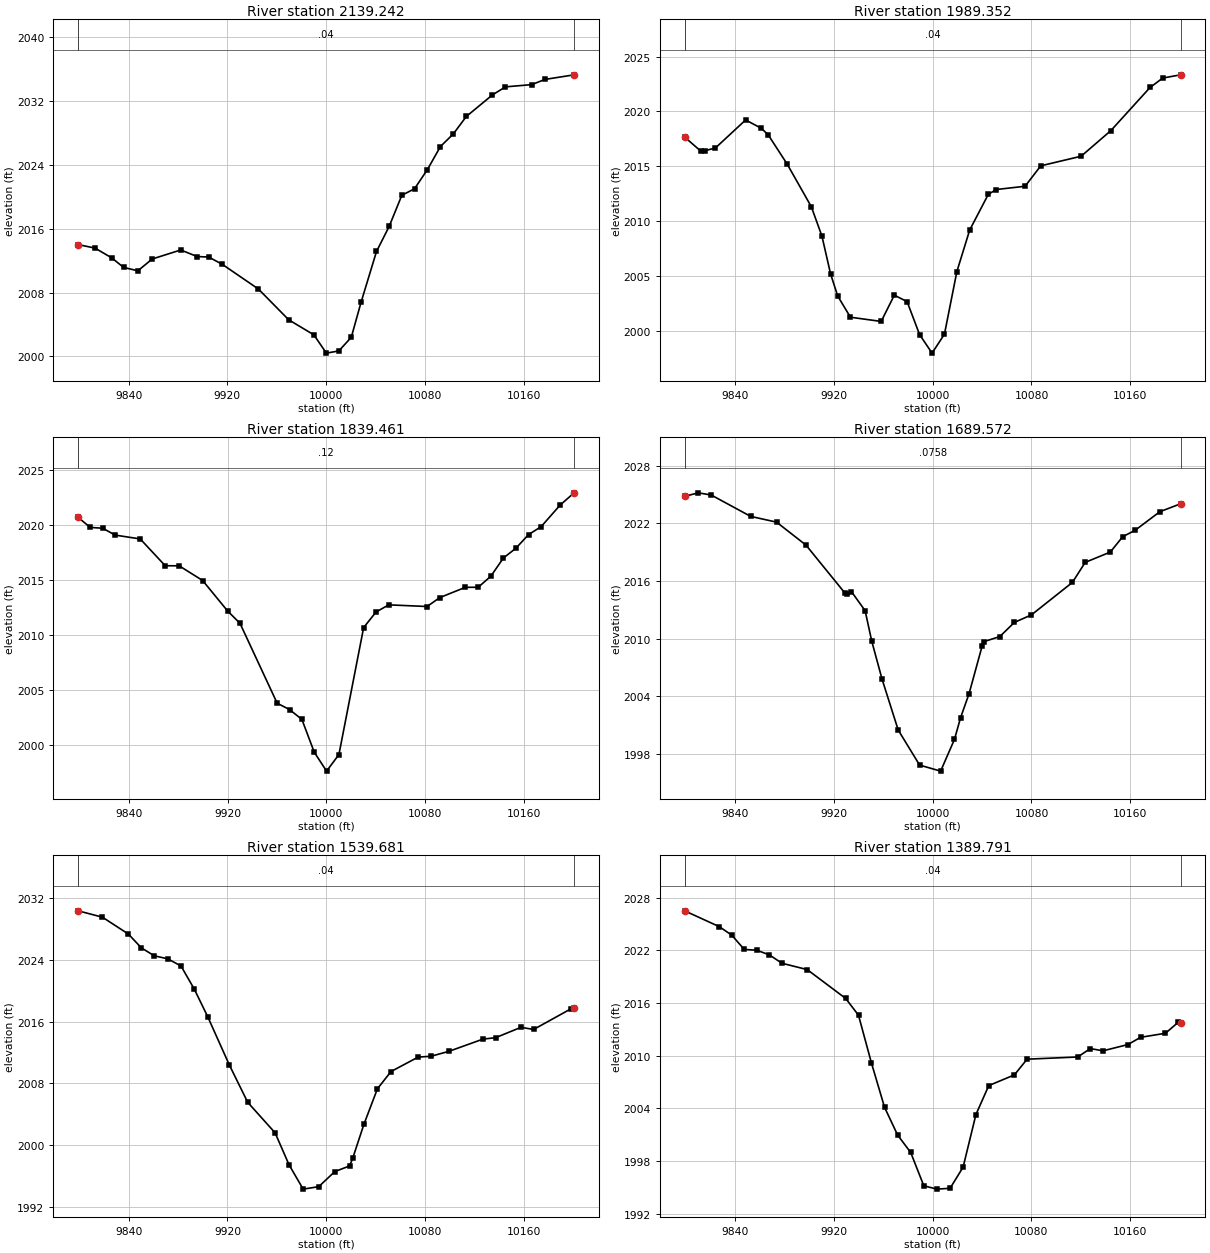
Type RM Length L Ch R = 1 ,2139.242,149.890000,149.890000,149.890000
XS GIS Cut Line= 6
703633.255546255763851.329348567703716.498631588 763899.93063715
703761.396479466 763921.04773559703791.244278765763929.554537599
 703885.08332707763947.129572313704007.260329177763989.282847791
#Sta/Elev= 30
 9799.092014.0069812.6892013.5699826.2032012.3499835.849 2011.159847.428 2010.72
9859.008  2012.29882.1672013.3329895.482 2012.519904.8772012.4469915.9282011.523
9945.0982008.4389969.6422004.581 9990.062002.69310000.172000.40110010.272000.674
10020.382002.38910028.262006.761 10040.82013.14210051.07 2016.2910061.342020.193
10071.612021.006 10082.12023.42110092.592026.29710103.09 2027.8910113.582030.067
10134.692032.76610145.332033.78210166.622034.06410177.272034.71510200.972035.291
#Mann= 3 , 0 , 0
 9799.09    0.04       0 9799.09    0.04       010200.97    0.04       0
#XS Ineff= 2 , 0
       0                               0
Bank Sta=9799.09,10200.97
Exp/Cntr=0.3,0.1

Type RM Length L Ch R = 1 ,1989.352,149.890100,149.890100,149.890100
XS GIS Cut Line= 6
703594.365878536763875.596313843703695.299721337763963.466542595
703723.434798867764066.118429027703747.801723435764105.172390688
703791.579725936764134.493869188703849.026608929764151.832137764
#Sta/Elev= 30
9799.1512017.6559811.9862016.3989815.9462016.4269824.0562016.6629848.506 2019.22
9861.3122018.4519866.7832017.8619882.2012015.1859901.7152011.3029910.2712008.634
9917.2962005.1819923.0422003.1659933.3732001.2249958.2852000.839 9968.932003.236
9979.2862002.6449989.3891999.6389999.4871997.94810009.53 1999.6810019.582005.388
10029.952009.17510044.992012.42210051.412012.87310074.81 2013.1710087.542015.035
10120.21 2015.9110144.342018.253   10176 2022.1810186.322023.04310200.782023.336
#Mann= 3 , 0 , 0
9799.151    0.04       09799.151    0.04       010200.78    0.04       0
#XS Ineff= 2 , 0
       09964.422                       0
Bank Sta=9799.151,10200.78
Exp/Cntr=0.3,0.1

Type RM Length L Ch R = 1 ,1839.461,149.890000,149.890000,149.890000
XS GIS Cut Line= 6
703425.441427809764095.241160292703506.115349378764108.730496329
703562.607506299764116.216669372703666.130955669764121.045633195
703749.822231018764143.367897667703821.304519852764157.110577942
#Sta/Elev= 30
9799.0172020.6819808.7082019.7749818.8472019.6989828.9862019.0759849.2632018.729
9869.5412016.2969880.8112016.291 9899.862014.9579920.0352012.2019930.1232011.074
9960.2512003.8299970.2792003.2539980.2852002.3619990.2851999.38910000.29 1997.67
10010.291999.17310030.32 2010.6910040.382012.10210050.69 2012.7510081.74  2012.6
10092.092013.41210112.792014.34110123.142014.343 10133.42015.34810143.59    2017
10153.772017.89110163.952019.12110174.142019.83910189.742021.82110200.92 2022.91
#Mann= 3 , 0 , 0
9799.017    0.12       09799.017    0.12       010200.92    0.12       0
#XS Ineff= 2 , 0
       0                               0
Bank Sta=9799.017,10200.92
Exp/Cntr=0.3,0.1

Type RM Length L Ch R = 1 ,1689.572,149.890100,149.890100,149.890100
XS GIS Cut Line= 6
703504.455213423764361.026285823703620.859438718764306.131184451
703685.811463575764215.114211347703721.523310243764186.002926811
703771.865495717764170.301132596703831.870822152 764169.46641769
#Sta/Elev= 30
9799.1062024.8129810.1682025.1769820.6592024.9459852.5662022.7229873.5212022.124
9897.3672019.7329928.6322014.7829930.322 2014.599934.2042014.8889945.2632012.903
9950.603 2009.749959.0152005.7589972.0592000.4759989.4081996.82410006.431996.196
10017.641999.50710022.542001.74510029.462004.26310040.072009.23910041.662009.692
10054.312010.20310066.192011.68510079.962012.46510113.142015.84610123.532017.935
10143.882019.007 10153.92020.60910163.922021.27110183.932023.20610200.812024.036
#Mann= 3 , 0 , 0
9799.106  0.0758       09799.106  0.0758       010200.81  0.0758       0
#XS Ineff= 2 , 0
       0                               0
Bank Sta=9799.106,10200.81
Exp/Cntr=0.3,0.1

Type RM Length L Ch R = 1 ,1539.681,149.890000,149.890000,149.890000
XS GIS Cut Line= 6
703566.316521101764436.983226029 703703.85204063764385.728013112
703770.914118173 764342.57251536703813.574024499764322.989628815
703872.810389005764304.223609359703937.460706231764292.182771354
#Sta/Elev= 30
9799.0992030.3429818.7282029.516 9839.742027.3369850.2462025.5519860.7522024.516
9871.5392024.1369882.3522023.2049893.1642020.1999903.976 2016.659921.6052010.365
9936.4142005.558 9958.612001.6059969.9341997.4589981.3531994.3179993.9571994.636
10006.991996.59110018.99 1997.3210021.531998.33310030.522002.68710041.522007.313
10052.52 2009.5410074.462011.40610084.952011.51810099.422012.15310126.912013.731
10137.342013.92710157.842015.26510168.022014.982 10198.42017.66810200.892017.711
#Mann= 3 , 0 , 0
9799.099    0.04       09799.099    0.04       010200.89    0.04       0
#XS Ineff= 2 , 0
       0                               0
Bank Sta=9799.099,10200.89
Exp/Cntr=0.3,0.1

Type RM Length L Ch R = 1 ,1389.791,63.041700,63.041700,63.041700
XS GIS Cut Line= 6
703586.954692949764541.588618373703632.853452909764537.489021842
703680.732092724764528.230558701703844.335929189764476.490232317
703917.737035383 764459.75648307703977.129820173764450.664358158
#Sta/Elev= 30
9799.0612026.4929827.2182024.6819837.2582023.7159847.3292022.0989857.5142022.002
9867.6992021.4769877.8852020.5229898.3442019.7999929.5272016.5149939.922  2014.6
9950.4222009.1579961.0272004.1179971.6322000.9519982.2371998.9689992.8421995.175
10003.491994.79610014.141994.89110024.681997.29410035.082003.28710045.482006.587
10066.272007.80810076.532009.59510117.562009.84510127.812010.80310138.072010.548
10158.342011.26510168.462012.08510188.692012.54710198.812013.77510200.962013.754
#Mann= 3 , 0 , 0
9799.061    0.04       09799.061    0.04       010200.96    0.04       0
#XS Ineff= 2 , 0
       0                               0
Bank Sta=9799.061,10200.96
Exp/Cntr=0.3,0.1

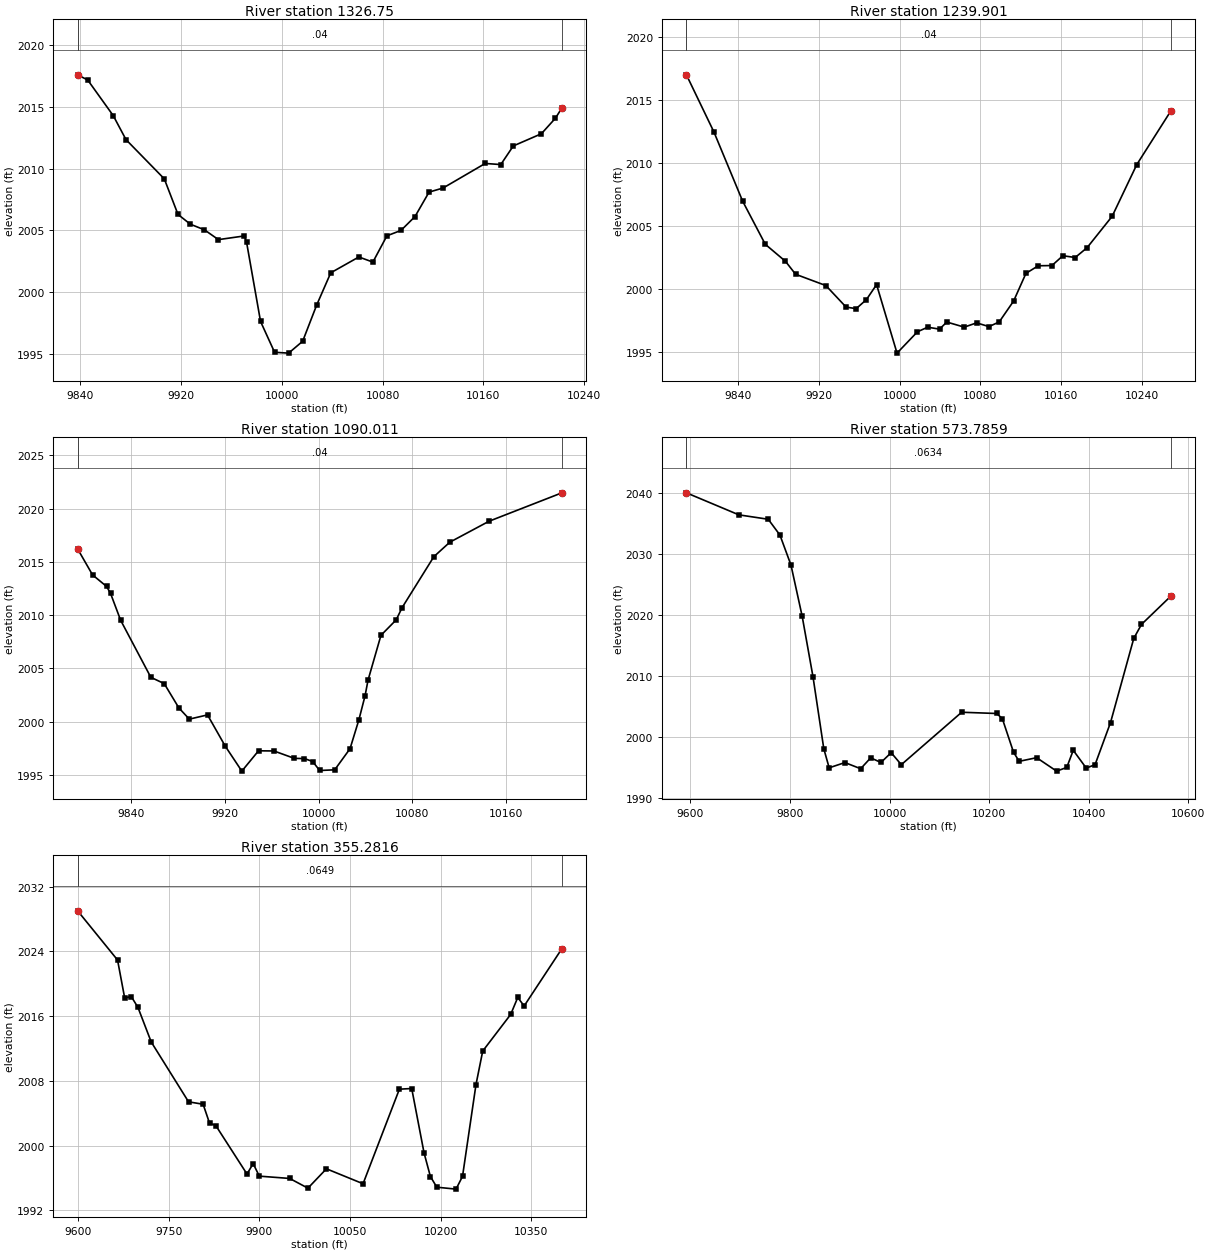
Type RM Length L Ch R = 1 , 1326.75,86.848400,86.848400,86.848400
XS GIS Cut Line= 3
703657.100144744764572.145377144703740.992825657764585.858603835
704009.610736609764453.566299364
#Sta/Elev= 30
9837.9042017.6079845.9082017.1879866.1742014.3019876.3072012.3579906.7052009.181
9917.5872006.2989927.3772005.5089938.5242005.0549949.6712004.2599970.1212004.555
9971.9642004.0799983.1111997.6319994.2581995.13310005.411995.06510016.551996.027
 10027.71998.96710038.852001.57110061.142002.85310072.292002.43910083.432004.567
10094.582005.00310105.732006.12810116.882008.10710128.022008.43910161.462010.428
10173.822010.33810183.762011.84710206.052012.834 10217.22014.09410222.342014.925
#Mann= 3 , 0 , 0
9837.904    0.04       09837.904    0.04       010222.34    0.04       0
#XS Ineff= 2 , 0
       0                               0
Bank Sta=9837.904,10222.34
Exp/Cntr=0.3,0.1

Type RM Length L Ch R = 1 ,1239.901,149.890000,149.890000,149.890000
XS GIS Cut Line= 6
703657.100144744764585.858603835703707.264712811764635.311117828
703760.209922969764638.084227562703806.485410392764635.985799924
703877.221858263764624.666433111704072.530247301764487.446035847
#Sta/Elev= 30
9788.7042017.0219815.9692012.4829844.4582006.9859866.8912003.5629886.9192002.208
9896.9322001.1829926.9682000.2849946.9891998.5749956.999 1998.459967.1111999.164
9977.2412000.3599997.5021994.91810017.751996.61410027.871996.97710039.651996.824
10046.851997.38610064.151996.98310076.411997.32110088.671997.025 10098.81997.396
10113.111999.05810125.322001.25410137.522001.85610151.082001.87410161.942002.654
10174.152002.51210185.942003.29310210.782005.785 10235.22009.89210268.822014.134
#Mann= 3 , 0 , 0
9788.704    0.04       09788.704    0.04       010268.82    0.04       0
#XS Ineff= 2 , 0
       09963.627        10047.35       0
Bank Sta=9788.704,10268.82
Exp/Cntr=0.3,0.1

Type RM Length L Ch R = 1 ,1090.011,516.225400,516.225400,516.225400
XS GIS Cut Line= 6
703649.552363584764604.346491102703720.975134939764700.842731594
703745.976292749764726.259357457703834.570831635764801.206289671
703861.381501179764830.663790372703917.264459889764915.398626002
#Sta/Elev= 30
9794.3482016.209  9807.12013.7699819.0692012.6849822.4552012.0299831.0472009.513
9856.8362004.1519868.2772003.5589880.7762001.2779889.6842000.2229905.233 2000.62
9920.3551997.6859934.5241995.3399948.7841997.2499961.9361997.2329979.4021996.536
9987.9991996.5199994.9971996.24110000.981995.398 10013.81995.46210026.891997.446
10034.492000.17610039.72 2002.4210042.262003.88510053.282008.09510066.262009.544
10071.392010.70610098.43 2015.4810112.062016.84110145.572018.81110207.752021.479
#Mann= 3 , 0 , 0
9794.348    0.04       09794.348    0.04       010207.75    0.04       0
#XS Ineff= 2 , 0
       0                               0
Bank Sta=9794.348,10207.75
Exp/Cntr=0.3,0.1

Type RM Length L Ch R = 1 ,573.7859,218.504300,218.504300,218.504300
XS GIS Cut Line= 6
703030.252009749764849.332973227703225.251464099764975.642113566
703521.439313948765060.308492139703635.990956932 765117.19401966
703699.386882991765155.318651572703874.906145066 765302.71555534
#Sta/Elev= 30
9591.882 2040.119697.2932036.498 9756.242035.7769779.7392033.1899801.9252028.267
9824.4362019.8679846.1722009.9529867.8981998.139 9878.651995.0219910.266 1995.88
 9941.921994.8729962.0751996.654 9982.691995.89410003.231997.50210023.571995.532
10144.872004.13210215.132003.92710226.472003.10110249.151997.55210260.491996.085
10295.46 1996.6810335.591994.47710355.981995.08110369.031997.89110395.151994.974
10412.841995.53610443.94 2002.4510490.592016.23710506.142018.53810564.792023.147
#Mann= 3 , 0 , 0
9591.882  0.0634       09591.882  0.0634       010564.79  0.0634       0
#XS Ineff= 2 , 0
       0                 10175.4       0
Bank Sta=9591.882,10564.79
Exp/Cntr=0.3,0.1

Type RM Length L Ch R = 1 ,355.2816,0.000000,0.000000,0.000000
XS GIS Cut Line= 6
703086.420949824765126.935777868703221.230623146765193.943581863
703359.125685426765235.348840441703546.014600229765222.780487363
703637.933681572765234.845979257703834.495921281765341.837547269
#Sta/Elev= 30
9599.1212029.0049665.1982022.931 9676.982018.252 9687.972018.4129698.9612017.081
9720.9432012.8069782.7682005.4169806.842 2005.129817.456 2002.799827.8452002.487
 9879.481996.4989889.7181997.7899899.8771996.2399950.1651995.9559980.3461994.755
10010.981997.14710071.63  1995.310131.772006.97910152.192007.06110172.621999.106
10183.111996.19310193.721994.87410225.541994.63610236.291996.21510258.582007.549
10269.722011.68710315.992016.20710327.722018.303 10338.32017.254 10400.82024.333
#Mann= 3 , 0 , 0
9599.121  0.0649       09599.121  0.0649       0 10400.8  0.0649       0
#XS Ineff= 2 , 0
       0                10147.39       0
Bank Sta=9599.121,10400.8
Exp/Cntr=0.3,0.1